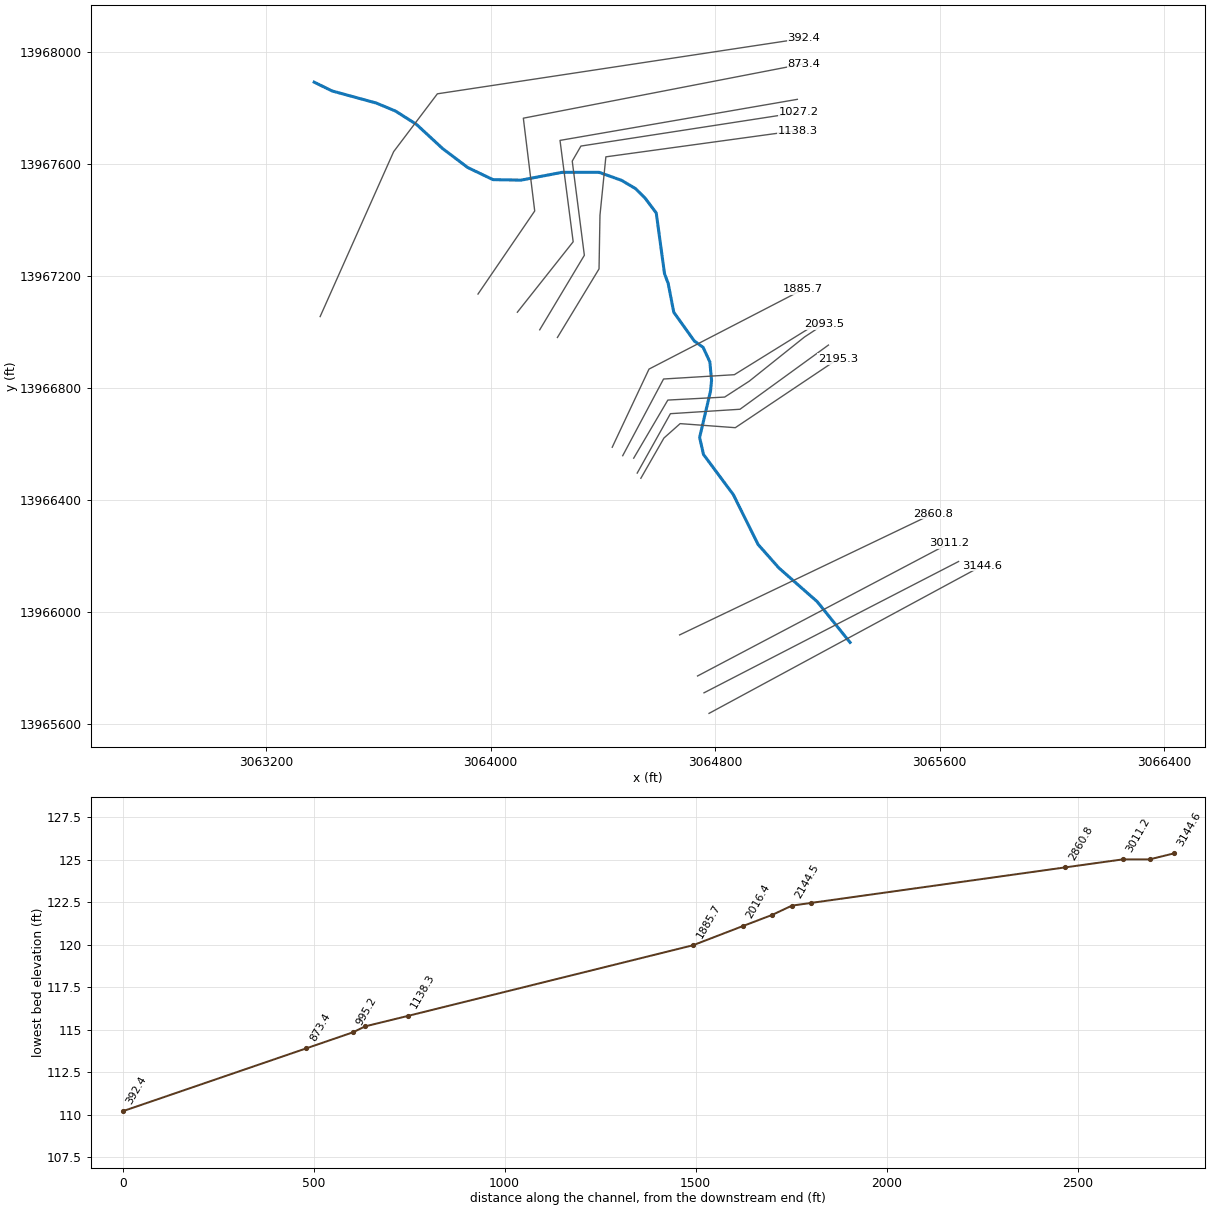
--- M108-00-00.PRJ (project) ---

Proj Title=M108-00-00
Current Plan=p03
Default Exp/Contr=.3,.1
English Units
Geom File=g01
Flow File=f02
Flow File=f03
Plan File=p02
Plan File=p03
Y Axis Title=Elevation
X Axis Title(PF)=Main Channel Distance
X Axis Title(XS)=Station
BEGIN DESCRIPTION:
Willow Creek
Hughes Gully
HCFCD Unit M108-00-00
Flood Hazard Model
10, 2, 1, 0.2% Event
Filename M108-00-00.prj
Prepared by: Halff Associates, Inc Date: 03/05/2004
Reviewed by:                  Date:
STATUS Final RAS
END DESCRIPTION:
DSS Export Rating Curves= 0
DSS Export Rating Curve Sorted= 0
DSS Export Volume Flow Curves= 0
DXF OffsetX= 0
DXF OffsetY= 0
DXF ScaleX= 1
DXF ScaleY= 10

--- M108-00-00.p03 (plan) ---

Plan Title=Floodway
Program Version=3.11
Short Identifier=Floodway0607
Geom File=g01
Flow File=f03
Subcritical Flow
K Sum by GR= 0
Std Step Tol= 0.01
Critical Tol= 0.01
Num of Std Step Trials= 20
Max Error Tol= 0.3
Flow Tol Ratio= 0.001
Split Flow NTrial= 30
Split Flow Tol= 0.02
Split Flow Ratio= 0.02
Log Output Level= 0
Friction Slope Method= 1
Unsteady Friction Slope Method= 2
Unsteady Bridges Friction Slope Method= 1
Parabolic Critical Depth
Global Vel Dist= 0 , 0 , 0
Global Log Level= 0
CheckData=True
Encroach Param=-1 ,0,0, 2
Encroach River=M108-00-00
Encroach Reach=M108-00-00_0004
Encroach Node=3144.6
       1 4958.18 5019.96
Encroach Node=3081.2
       1    4950    5045
Encroach Node=3046.2
       1    4950    5035
Encroach Node=3011.2
       1    4960 5023.67
Encroach Node=2860.8
       1 4975.93 5016.09
Encroach Node=2195.3
       1 4948.71 5061.59
Encroach Node=2144.5
       1 4953.66 5048.97
Encroach Node=2119.0
       1 4953.66 5048.97
Encroach Node=2093.5
       1 4953.66 5048.97
Encroach Node=2016.4
       1 4989.46 5009.08
Encroach Node=1885.7
       1 4990.87  5017.1
Encroach Node=1138.3
       1 4989.02 5014.83
Encroach Node=1027.2
       1 4986.63  5009.8
Encroach Node=1011.2
       1 4986.63  5009.8
Encroach Node=995.2
       1 4986.63  5009.8
Encroach Node=873.4
       1 4992.51 5013.95
Encroach Node=392.4
       1 4988.06 5010.17
Computation Interval=1HOUR
Output Interval=1HOUR
Run HTab= 0
Run UNet= 0
Run PostProcess= 0
UNET Theta= 1
UNET Theta Warmup= 1
UNET ZTol= 0.02
UNET ZSATol= 0.1
UNET MxIter= 20
UNET MaxInSteps= 20
UNET DtIC= 0
UNET DtMin= 0
UNET MaxCRTS= 20
UNET WFStab= 2
UNET SFStab= 1
UNET WFX= 1
UNET SFX= 1
UNET DSS MLevel= 4
UNET DZMax Abort= 100
UNET Convert EG Bridges=-1
UNET Use Existing IB Tables=-1
UNET Froude Reduction=False
UNET Froude Limit= 1
UNET Froude Power= 10
Instantaneous Interval=1HOUR
Write IC File= 0
Echo Input=False
Echo Output=False
Write Detailed= 0
Detailed Automatic Start=False, 10

--- M108-00-00.p02 (plan) ---

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Plan Title=FEMA Effective June 2007
Program Version=3.13
Short Identifier=FEMAeff0607
Geom File=g01
Flow File=f02
Encroach Param=-1 ,0,0, 0

--- M108-00-00.f03 (steady flow) ---

Flow Title=Floodway
Program Version=3.13
Number of Profiles= 2
Profile Names=1PCT_100yr,1PCTFloodway_100yrFW
River Rch & RM=M108-00-00,M108-00-00_0004 ,3144.6
     920     920
River Rch & RM=M108-00-00,M108-00-00_0004 ,2860.8
    1000    1000
River Rch & RM=M108-00-00,M108-00-00_0004 ,2144.5
    1100    1100
River Rch & RM=M108-00-00,M108-00-00_0004 ,1027.2
    1147    1147
Boundary for River Rch & Prof#=M108-00-00,M108-00-00_0004 , 1
Up Type= 0
Dn Type= 3
Dn Slope=0.0045
Boundary for River Rch & Prof#=M108-00-00,M108-00-00_0004 , 2
Up Type= 0
Dn Type= 1
Dn Known WS=121
DSS Import GetInterval= 0
DSS Import GetPeak= 0
DSS Import FillOption= 0

--- M108-00-00.f02 (steady flow) ---

Flow Title=FEMA Effective June 2007
Program Version=3.13
Number of Profiles= 4
Profile Names=10PCT_10yr, 2PCT_50yr, 1PCT_100yr,0.2PCT_500yr
River Rch & RM=M108-00-00,M108-00-00_0004 ,3144.6
     470     740     920    1450
River Rch & RM=M108-00-00,M108-00-00_0004 ,2860.8
     520     810    1000    1600
River Rch & RM=M108-00-00,M108-00-00_0004 ,2144.5
     560     900    1100    1650
River Rch & RM=M108-00-00,M108-00-00_0004 ,1027.2
     597     965    1147    1693
Boundary for River Rch & Prof#=M108-00-00,M108-00-00_0004 , 1
Up Type= 0
Dn Type= 3
Dn Slope=0.0045
Boundary for River Rch & Prof#=M108-00-00,M108-00-00_0004 , 2
Up Type= 0
Dn Type= 3
Dn Slope=0.0045
Boundary for River Rch & Prof#=M108-00-00,M108-00-00_0004 , 3
Up Type= 0
Dn Type= 3
Dn Slope=0.0045
Boundary for River Rch & Prof#=M108-00-00,M108-00-00_0004 , 4
Up Type= 0
Dn Type= 3
Dn Slope=0.0045
DSS Import GetInterval= 0
DSS Import GetPeak= 0
DSS Import FillOption= 0

--- M108-00-00.g01 (geometry) ---

Geom Title=M108-00-00 June 2007
Program Version=3.13

River Reach=M108-00-00      ,M108-00-00_0004
Reach XY= 30
      3065280.62     13965890.39       3065163.5       13966036.
      3065027.25       13966156.        3064953.       13966240.
      3064864.75       13966418.      3064758.53     13966561.22
      3064744.64     13966621.99       3064783.7     13966788.65
      3064787.18     13966825.98       3064781.1     13966891.95
        3064757.     13966943.95      3064725.78      13966966.5
      3064652.63     13967069.04      3064632.66      13967171.9
      3064619.64     13967206.62      3064590.13     13967423.64
      3064551.06     13967475.72      3064516.34     13967510.44
      3064466.86     13967539.96        3064387.      13967568.6
      3064254.19      13967568.6      3064108.36     13967540.82
      3064008.53     13967542.56      3063918.25     13967585.96
      3063828.84     13967653.67      3063735.29      13967740.3
      3063661.31     13967787.35      3063592.75       13967816.
      3063434.75      13967859.4      3063371.38     13967890.65

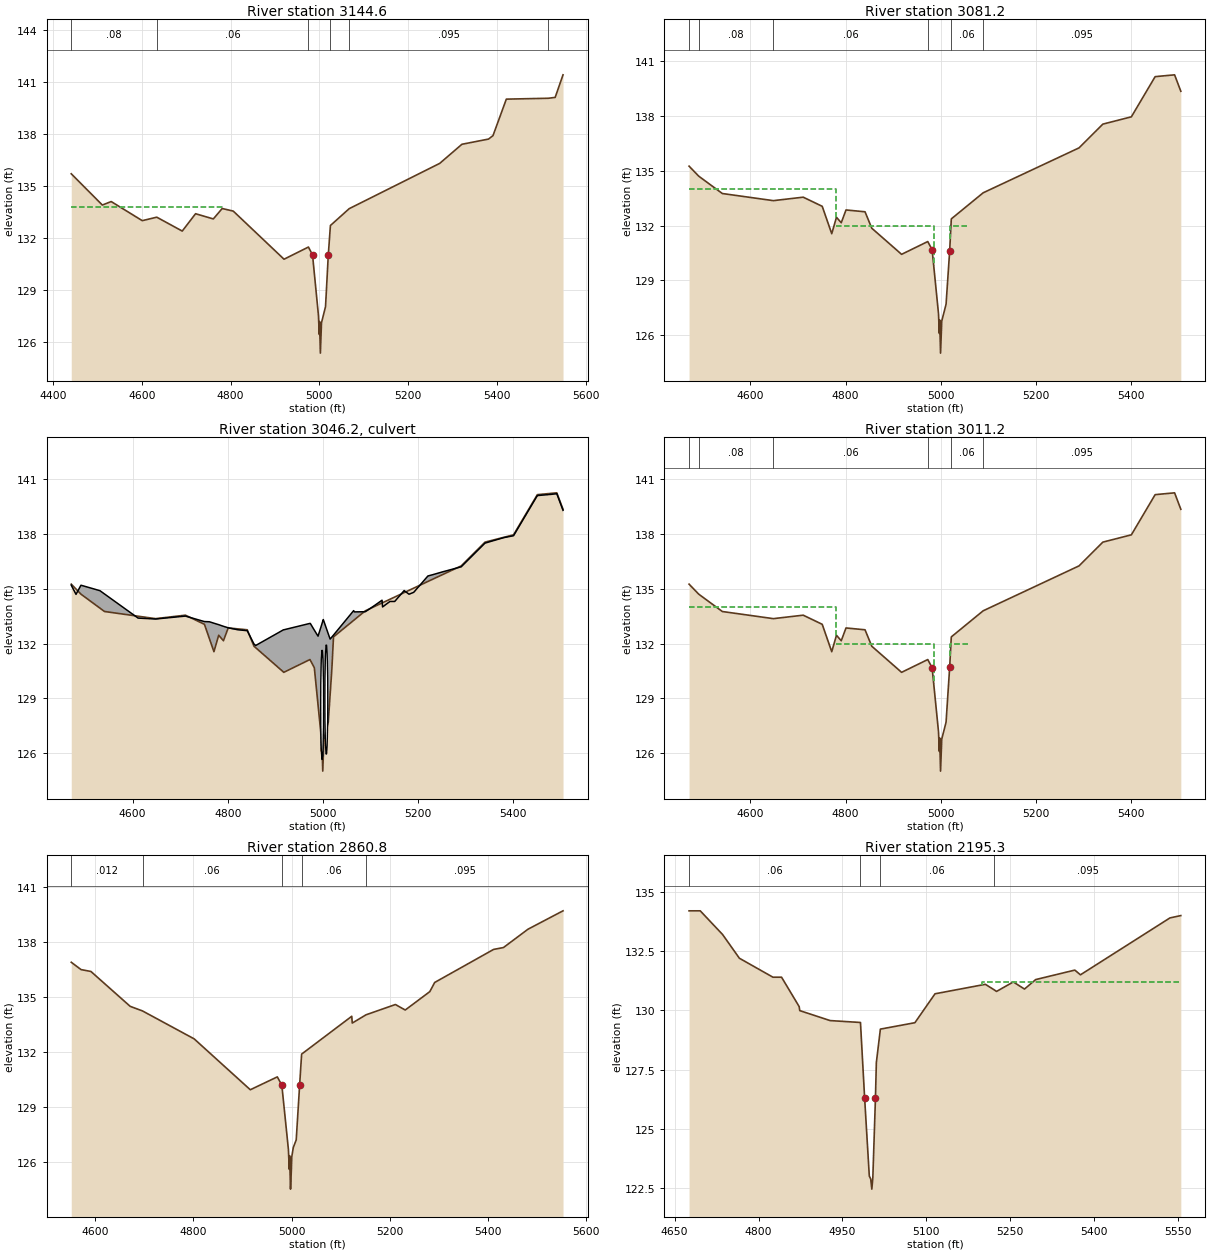
Type RM Length L Ch R = 1 ,3144.6  ,63.4,63.4,63.4
BEGIN DESCRIPTION:
Cross Section 3144.6
Cross Section XS-08-culvert2-con
END DESCRIPTION:
XS GIS Cut Line= 2
      3064778.22       13965637.      3065752.19      13966164.6
#Sta/Elev= 30
    4441   135.7    4511   133.9    4531   134.1    4601     133  4633.6   133.2
    4691   132.4    4721   133.4    4761   133.1    4781   133.7 4805.95  133.55
 4920.25  130.78 4975.25  131.48 4984.45  131.03 4997.85  127.53 4999.65  126.45
 5000.25  127.19 5002.15  125.37 5004.65  127.12 5013.75  128.05 5019.96  131.02
 5024.75  132.72    5067  133.69    5271   136.3    5321   137.4    5381   137.7
    5391   137.9    5421     140  5515.7  140.05    5531   140.1  5548.7   141.4
#Mann= 6 ,-1 , 0
    4441     .08       0  4633.6     .06       0 4975.25     .04       0
 5024.75     .06       0    5067    .095       0  5515.7     .15       0
#XS Ineff= 2 , 0
       0    4780   133.8               0
Permanent Ineff=
       F       F
Bank Sta=4984.45,5019.96
Exp/Cntr=0.5,0.3

Type RM Length L Ch R = 1 ,3081.2  ,70,70,70
BEGIN DESCRIPTION:
Upstream Section of Lenze Road Culvert
END DESCRIPTION:
XS GIS Cut Line= 2
      3064760.28      13965710.4      3065667.24      13966179.2
#Sta/Elev= 30
  4470.9  135.26  4491.3  134.71  4540.9  133.76  4648.2  133.37  4710.9  133.56
  4750.9  133.06  4770.9  131.56  4780.9  132.46  4790.9  132.16  4800.9  132.86
  4840.9  132.76  4855.1  131.86  4917.8  130.43  4972.8  131.13    4982  130.68
  4995.4  127.18  4997.2   126.1  4997.8  126.84  4999.7  125.02  5002.2  126.77
  5011.3   127.7 5018.92  130.63  5022.3  132.37  5089.3   133.8  5290.9  136.26
  5340.9  137.56  5400.9  137.96  5450.9  140.16  5491.8  140.26  5504.9  139.36
#Mann= 6 ,-1 , 0
  4470.9      .2       0  4491.3     .08       0  4648.2     .06       0
  4972.8     .04       0  5022.3     .06       0  5089.3    .095       0
#XS Ineff= 3 ,-1
  4470.9    4780     134    4780  4985.4     132  5020.2    5060     132
Permanent Ineff=
       T       F       F
Bank Sta=4982,5018.92
Exp/Cntr=0.5,0.3

Type RM Length L Ch R = 2 ,3046.2  ,,,
BEGIN DESCRIPTION:
LENZE ROAD
Cross Section 3046.2
Structure ID: M108-00-00-03
END DESCRIPTION:
Bridge Culvert--1,0,-1,-1, 0
Deck Dist Width WeirC Skew NumUp NumDn MinLoCord MaxHiCord MaxSubmerge Is_Ogee
10,50,3,0, 74, 74, , , 0.95, 0, 1,1,,
  4470.9  4480.9  4491.3  4500.9  4531.3  4540.9  4610.9  4611.3  4648.2  4710.9
  4750.9  4761.3  4770.9  4780.9  4790.9  4800.9  4821.3  4840.9  4855.1  4858.7
  4917.1  4917.8  4972.8  4973.5    4982  4989.8  4991.1  4995.4  4997.2  4997.8
  4999.7  5000.8  5001.2  5002.2  5005.4  5011.3  5015.2  5022.3  5064.7  5066.3
  5089.3  5101.3  5111.3  5124.4  5125.4  5140.9  5150.9  5151.3  5170.9  5171.3
  5180.9  5181.3  5190.9  5201.3  5220.9  5221.3  5231.3  5251.3  5261.3  5290.9
  5321.3  5331.3  5340.9  5341.3  5380.9  5400.9  5401.3  5421.3  5431.3  5450.9
  5451.3  5481.3  5491.8  5504.9
   135.2   134.7   135.2  135.13   134.9  134.72  133.41   133.4  133.35  133.51
  133.21   133.2  133.12  133.04  132.95  132.87  132.76  132.71  131.98   131.9
  132.76  132.76  133.11  133.11  132.74  132.41  132.52  132.87  133.02  133.07
  133.23  133.32  133.29  133.22  132.98  132.54  132.25  132.47  133.81  133.74
  133.75  133.96  134.14  134.38  134.01  134.31  134.31  134.32  134.91   134.9
  134.71  134.71  134.81  135.12  135.71  135.71  135.78  135.93     136  136.21
     137  137.26  137.51  137.51  137.81  137.91  137.93  138.81  139.25  140.11
  140.11  140.18  140.21   139.3
                                                                                
                                                                                
                                                          127.12  126.04  126.78
  124.96  125.66  125.92  126.71  127.23
                                                                                
                                                                                
                                                                                
                                
  4470.9  4480.9  4491.3  4500.9  4531.3  4540.9  4610.9  4611.3  4648.2  4710.9
  4750.9  4761.3  4770.9  4780.9  4790.9  4800.9  4821.3  4840.9  4855.1  4858.7
  4917.1  4917.8  4972.8  4973.5    4982  4989.8  4991.1  4995.4  4997.2  4997.8
  4999.7  5000.8  5001.2  5002.2  5005.4  5011.3  5015.2  5022.3  5064.7  5066.3
  5089.3  5101.3  5111.3  5124.4  5125.4  5140.9  5150.9  5151.3  5170.9  5171.3
  5180.9  5181.3  5190.9  5201.3  5220.9  5221.3  5231.3  5251.3  5261.3  5290.9
  5321.3  5331.3  5340.9  5341.3  5380.9  5400.9  5401.3  5421.3  5431.3  5450.9
  5451.3  5481.3  5491.8  5504.9
  135.29  134.79   135.2  135.13   134.9  134.72  133.41   133.4   133.4  133.59
  133.21   133.2  133.12  133.04  132.95  132.89  132.84  132.79  131.98   131.9
  132.76  132.76  133.11  133.11  132.74  132.41  132.52  132.87  133.02  133.07
  133.23  133.32  133.29  133.22  132.98  132.54  132.25  132.47  133.81  133.74
  133.83  134.04  134.22  134.46  134.09  134.39  134.39   134.4  134.99  134.98
  134.79  134.79  134.89   135.2  135.79  135.79  135.86  136.01  136.08  136.29
  137.08  137.34  137.59  137.59  137.89  137.99  138.01  138.89  139.33  140.19
  140.19  140.26  140.29  139.39
                                                                                
                                                                                
                                                          127.21  126.13  126.87
  125.05  125.75  126.01   126.8  127.32
                                                                                
                                                                                
                                                                                
                                
BR Coef= 1 , 0 , 0 ,1.25, 0 ,,,0.8,-1,2,0,
WSPro=,,,, 1 ,,,, 0 ,,,, 0 ,,,,-1 ,-1 ,-1 , 0 , 0 , 0 , 0 , 0
Culvert=1,6,,50,0.015,0.5,1,1,3,125.65,4998.4,125.4,4998.4,Culvert #1  , 0 ,10
Culvert Bottom n=0.015
Culvert=1,6,,50,0.015,0.5,1,1,3,125.94,5007.2,125.46,5007.2,Culvert #2  , 0 ,10
Culvert Bottom n=0.015
BC Design=,, 0 ,, 0 ,,,,,,
BC HTab HWMax=140.26

Type RM Length L Ch R = 1 ,3011.2  ,150.4,150.4,150.4
BEGIN DESCRIPTION:
Downstream Section of Lenze Road Culvert
END DESCRIPTION:
XS GIS Cut Line= 2
      3064737.33      13965770.5      3065633.52       13966244.
#Sta/Elev= 30
  4470.9  135.26  4491.3  134.71  4540.9  133.76  4648.2  133.37  4710.9  133.56
  4750.9  133.06  4770.9  131.56  4780.9  132.46  4790.9  132.16  4800.9  132.86
  4840.9  132.76  4855.1  131.86  4917.8  130.43  4972.8  131.13    4982  130.68
  4995.4  127.18  4997.2   126.1  4997.8  126.84  4999.7  125.02  5002.2  126.77
  5011.3   127.7 5018.86   130.7  5022.3  132.37  5089.3   133.8  5290.9  136.26
  5340.9  137.56  5400.9  137.96  5450.9  140.16  5491.8  140.26  5504.9  139.36
#Mann= 6 ,-1 , 0
  4470.9      .2       0  4491.3     .08       0  4648.2     .06       0
  4972.8     .04       0  5022.3     .06       0  5089.3    .095       0
#XS Ineff= 3 ,-1
  4470.9    4780     134    4780  4985.4     132  5020.2    5060     132
Permanent Ineff=
       T       F       F
Bank Sta=4982,5018.86
Exp/Cntr=0.5,0.3

Type RM Length L Ch R = 1 ,2860.8  ,677.81,665.5,618.24
BEGIN DESCRIPTION:
Cross Section 2860.8
Cross Section XS-07-culvert2-exp
END DESCRIPTION:
XS GIS Cut Line= 2
      3064673.37      13965917.1      3065576.31       13966350.
#Sta/Elev= 30
  4551.1   136.9  4571.1   136.5  4591.1   136.4  4671.1   134.5  4696.2  134.25
 4801.35  132.73 4915.65  129.96 4970.65  130.66 4979.85  130.21 4993.25  126.71
 4995.05  125.63 4995.65  126.37 4997.55  124.55 4999.15  125.51 5000.05   126.3
 5003.25  126.82 5009.15  127.23 5016.09  130.21 5020.15   131.9 5122.25  133.96
 5123.25  133.59  5151.3  134.04  5211.1   134.6  5231.1   134.3  5281.1   135.3
  5291.1   135.8  5411.1   137.6  5431.1   137.7  5481.1   138.7  5552.4   139.7
#Mann= 5 ,-1 , 0
  4551.1    .012       0  4696.2     .06       0 4979.85     .04       0
 5020.15     .06       0  5151.3    .095       0
Bank Sta=4979.85,5016.09
Exp/Cntr=0.3,0.1

Type RM Length L Ch R = 1 ,2195.3  ,50.1,50.8,65.36
BEGIN DESCRIPTION:
Cross Section 2195.3
Cross Section XS-06-culvert1-con
END DESCRIPTION:
XS GIS Cut Line= 5
      3064535.37      13966476.5      3064617.47       13966620.
      3064675.27      13966671.5       3064871.8       13966657.
      3065236.81       13966902.
#Sta/Elev= 30
  4675.7   134.2  4695.7   134.2  4735.7   133.2  4765.7   132.2  4825.7   131.4
  4841.1   131.4  4872.6  130.16  4873.7  129.99    4928  129.57  4982.2  129.49
 4989.62  126.31    4998  123.01  5000.5  122.89  5002.5  122.46  5004.3  122.94
 5008.97  126.29  5010.6   127.8  5017.8  129.21  5079.5  129.48  5115.5   130.7
  5205.5   131.1  5221.1  130.87  5225.5   130.8  5255.5   131.2  5275.5   130.9
  5295.5   131.3  5365.5   131.7  5375.5   131.5  5535.5   133.9    5555     134
#Mann= 4 ,-1 , 0
  4675.7     .06       0  4982.2     .04       0  5017.8     .06       0
  5221.1    .095       0
#XS Ineff= 2 , 0
       0                    5200       0   131.2
Permanent Ineff=
       F       F
Bank Sta=4989.62,5008.97
Exp/Cntr=0.5,0.3

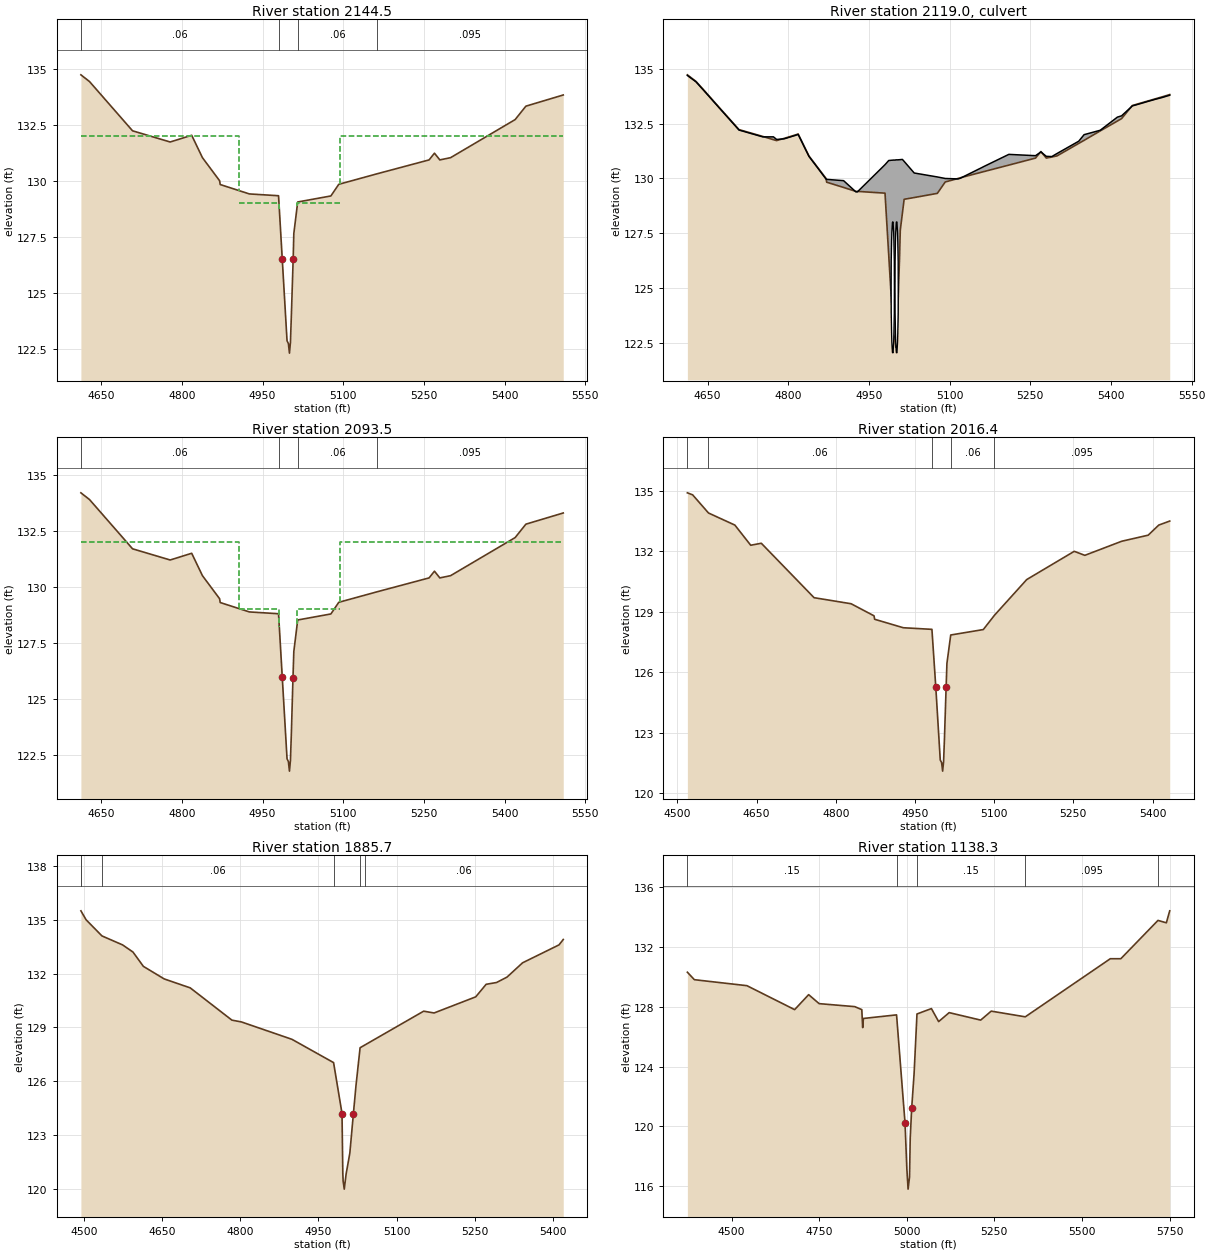
Type RM Length L Ch R = 1 ,2144.5  ,51,51,51
BEGIN DESCRIPTION:
Upstream Section of Access Road Culvert
END DESCRIPTION:
XS GIS Cut Line= 4
       3064522.3      13966494.9      3064640.64       13966707.
      3064888.57      13966722.8      3065203.61       13966952.
#Sta/Elev= 29
  4612.3  134.73  4628.3  134.43  4708.3  132.23  4778.3  131.73  4818.3  132.03
  4838.3  131.03  4870.2     130  4871.3  129.83  4925.6  129.41  4979.8  129.33
  4986.7   126.5  4995.6  122.85  4998.1  122.73  5000.1   122.3  5001.9  122.78
  5003.5  123.89 5006.99   126.5  5008.2  127.64  5015.4  129.05  5077.1  129.32
  5091.8  129.84  5163.1  130.31  5259.7  130.93  5269.7  131.23  5279.7  130.93
  5299.7  131.03  5419.7  132.73  5439.7  133.33  5509.2  133.83
#Mann= 4 ,-1 , 0
  4612.3     .06       0  4979.8     .04       0  5015.4     .06       0
  5163.1    .095       0
#XS Ineff= 4 ,-1
  4612.3    4906     132    4906  4981.2     129  5014.4    5094     129
    5094  5509.2     132
Permanent Ineff=
       T       F       F       T
Bank Sta=4986.7,5006.99
Exp/Cntr=0.5,0.3

Type RM Length L Ch R = 2 ,2119.0  ,,,
BEGIN DESCRIPTION:
ACCESS PRIVATE GRAVEL ROAD
Cross Section 2119.0
Structure ID: M108-00-00-02
END DESCRIPTION:
Bridge Culvert--1,0,-1,-1, 0
Deck Dist Width WeirC Skew NumUp NumDn MinLoCord MaxHiCord MaxSubmerge Is_Ogee
10,31,3,0, 53, 53, , , 0.95, 0, 1,1,,
  4612.3  4628.3  4642.3  4672.3  4692.3  4708.3  4752.3  4772.3  4778.3  4792.3
  4812.3  4818.3  4838.3  4852.8  4870.2  4871.3  4902.8  4925.6  4928.5  4979.8
  4986.7  4995.6  4998.1  4998.7  5000.1  5001.2  5001.9  5003.5  5008.2  5012.1
  5015.4  5034.1  5077.1  5091.8  5115.6  5119.7    5160  5163.1    5210  5259.7
  5269.7  5279.7    5290  5299.7    5340    5350    5380  5411.9  5419.7  5439.7
  5481.9  5495.9  5509.2
   134.7  134.41  134.03   133.2  132.65  132.21   131.9   131.9  131.78  131.81
  131.96  132.01  131.01  130.54  129.97  129.96   129.9  129.39  129.39  130.63
  130.82  130.84  130.84  130.84  130.85  130.85  130.85  130.85  130.86  130.87
  130.78  130.25  130.07     130  129.98  130.01   130.5  130.54   131.1  131.04
  131.21  131.01     131  131.14   131.7     132   132.2   132.8  132.86  133.31
  133.61   133.7   133.8
                                                                                
                                                                                
          122.82   122.7  122.54  122.27  122.59  122.75  123.86
                                                                                
                                                                                
                        
  4612.3  4628.3  4642.3  4672.3  4692.3  4708.3  4752.3  4772.3  4778.3  4792.3
  4812.3  4818.3  4838.3  4852.8  4870.2  4871.3  4902.8  4925.6  4928.5  4979.8
  4986.7  4995.6  4998.1  4998.7  5000.1  5001.2  5001.9  5003.5  5008.2  5012.1
  5015.4  5034.1  5077.1  5091.8  5115.6  5119.7    5160  5163.1    5210  5259.7
  5269.7  5279.7    5290  5299.7    5340    5350    5380  5411.9  5419.7  5439.7
  5481.9  5495.9  5509.2
   134.7  134.41  134.03   133.2  132.65  132.21   131.9   131.9  131.78  131.81
  131.96  132.01  131.01  130.54  129.97  129.96   129.9  129.39  129.39  130.63
  130.82  130.84  130.84  130.84  130.85  130.85  130.85  130.85  130.86  130.87
  130.78  130.25  130.07     130  129.98  130.01   130.5  130.54   131.1  131.04
  131.21  131.01     131  131.14   131.7     132   132.2   132.8  132.86  133.31
  133.61   133.7   133.8
                                                                                
                                                                                
           122.4  122.28  122.12  121.85  122.17  122.33  123.44
                                                                                
                                                                                
                        
BR Coef= 1 , 0 , 0 ,1.25, 0 ,,,0.8,-1,2,0,
WSPro=,,,, 1 ,,,, 0 ,,,, 0 ,,,,-1 ,-1 ,-1 , 0 , 0 , 0 , 0 , 0
Culvert=1,6,,31,0.027,0.9,1,1,3,122.03,4994.2,121.39,4994.2,Culvert #1  , 0 ,10
Culvert Bottom n=0.027
Culvert=1,6,,31,0.027,0.9,1,1,3,122.03,5001.4,121.35,5001.4,Culvert #2  , 0 ,10
Culvert Bottom n=0.027
BR U #Sta/Elev= 54
  4612.3  134.73  4628.3  134.43  4642.3  134.05  4672.3  133.22  4692.3  132.67
  4708.3  132.23  4752.3  131.92  4772.3  131.77  4778.3  131.73  4792.3  131.83
  4812.3  131.98  4818.3  132.03  4838.3  131.03  4852.8  130.56  4870.2     130
  4871.3  129.83  4902.8  129.59  4925.6  129.41  4928.5  129.41  4979.8  129.33
  4986.7   126.5  4995.6  122.85  4998.1  122.73  4998.7  122.57  5000.1   122.3
  5001.2  122.62  5001.9  122.78  5003.5  123.89 5006.99   126.5  5008.2  127.64
  5012.1   128.4  5015.4  129.05  5034.1  129.13  5077.1  129.32  5091.8  129.84
  5115.6     130  5119.7  130.03    5160  130.29  5163.1  130.31    5210  130.61
  5259.7  130.93  5269.7  131.23  5279.7  130.93    5290  130.98  5299.7  131.03
    5340   131.6    5350  131.74    5380  132.17  5411.9  132.62  5419.7  132.73
  5439.7  133.33  5481.9  133.63  5495.9  133.73  5509.2  133.83
BR U #Mann= 4
  4612.3     .06  4979.8     .04  5015.4     .06  5163.1    .095
BR D #Sta/Elev= 54
  4612.3  134.19  4628.3  133.89  4642.3  133.51  4672.3  132.68  4692.3  132.13
  4708.3  131.69  4752.3  131.38  4772.3  131.23  4778.3  131.19  4792.3  131.29
  4812.3  131.44  4818.3  131.49  4838.3  130.49  4852.8  130.02  4870.2  129.46
  4871.3  129.29  4902.8  129.05  4925.6  128.87  4928.5  128.87  4979.8  128.79
  4986.7  125.96  4995.6  122.31  4998.1  122.19  4998.7  122.03  5000.1  121.76
  5001.2  122.08  5001.9  122.24  5003.5  123.35 5006.63  125.92  5008.2   127.1
  5012.1  127.86  5015.4  128.51  5034.1  128.59  5077.1  128.78  5091.8   129.3
  5115.6  129.46  5119.7  129.49    5160  129.75  5163.1  129.77    5210  130.07
  5259.7  130.39  5269.7  130.69  5279.7  130.39    5290  130.44  5299.7  130.49
    5340  131.06    5350   131.2    5380  131.63  5411.9  132.08  5419.7  132.19
  5439.7  132.79  5481.9  133.09  5495.9  133.19  5509.2  133.29
BR D #Mann= 4
  4612.3     .06  4979.8     .04  5015.4     .06  5163.1    .095
BC Design=,, 0 ,, 0 ,,,,,,
BC HTab HWMax=134.73

Type RM Length L Ch R = 1 ,2093.5  ,77.1,77.1,77.1
BEGIN DESCRIPTION:
Downstream Section of Access Road Culvert
END DESCRIPTION:
XS GIS Cut Line= 6
      3064509.81      13966548.2      3064631.44      13966755.6
      3064833.93      13966766.3      3064921.55      13966823.1
      3065118.11      13966980.6      3065188.25      13967026.9
#Sta/Elev= 29
  4612.3  134.19  4628.3  133.89  4708.3  131.69  4778.3  131.19  4818.3  131.49
  4838.3  130.49  4870.2  129.46  4871.3  129.29  4925.6  128.87  4979.8  128.79
  4986.7  125.96  4995.6  122.31  4998.1  122.19  5000.1  121.76  5001.9  122.24
  5003.5  123.35 5006.63  125.92  5008.2   127.1  5015.4  128.51  5077.1  128.78
  5091.8   129.3  5163.1  129.77  5259.7  130.39  5269.7  130.69  5279.7  130.39
  5299.7  130.49  5419.7  132.19  5439.7  132.79  5509.2  133.29
#Mann= 4 ,-1 , 0
  4612.3     .06       0  4979.8     .04       0  5015.4     .06       0
  5163.1    .095       0
#XS Ineff= 4 ,-1
  4612.3    4906     132    4906  4981.2     129  5014.4    5094     129
    5094  5509.2     132
Permanent Ineff=
       T       F       F       T
Bank Sta=4986.7,5006.63
Exp/Cntr=0.5,0.3

Type RM Length L Ch R = 1 ,2016.4  ,117.12,130.7,142.11
BEGIN DESCRIPTION:
Cross Section 2016.4
Cross Section XS-05-culvert1-exp
END DESCRIPTION:
XS GIS Cut Line= 4
      3064470.68       13966557.      3064616.16      13966830.8
      3064868.37      13966846.2      3065166.38      13967031.3
#Sta/Elev= 30
    4519   134.9    4529   134.8    4559   133.9    4609   133.3    4639   132.3
    4659   132.4    4759   129.7  4829.1   129.4  4872.6   128.8  4873.7  128.63
    4928  128.21  4982.2  128.13 4989.46  125.29    4998  121.65  5000.5  121.53
  5002.5   121.1  5004.3  121.58  5005.9  122.69 5009.08  125.25  5010.6  126.44
  5017.8  127.85  5079.5  128.12  5100.7  128.83  5161.8   130.6  5251.8     132
  5271.8   131.8  5341.8   132.5  5391.8   132.8  5411.8   133.3  5432.6   133.5
#Mann= 5 ,-1 , 0
    4519      .1       0    4559     .06       0  4982.2     .04       0
  5017.8     .06       0  5100.7    .095       0
Bank Sta=4989.46,5009.08
Exp/Cntr=0.5,0.3

Type RM Length L Ch R = 1 ,1885.7  ,711.23,747.4,770.26
BEGIN DESCRIPTION:
Cross Section 1885.7
Cross Section XS-04
END DESCRIPTION:
XS GIS Cut Line= 3
      3064433.31      13966587.2      3064564.36      13966866.2
      3065113.19      13967150.6
#Sta/Elev= 30
  4493.8   135.5  4503.8     135  4534.2   134.1  4573.8   133.6  4593.8   133.2
  4613.8   132.4  4653.8   131.7  4703.8   131.2  4783.8   129.4  4802.1   129.3
  4899.1  128.33  4979.1  127.03  4995.3  124.19  4996.8  120.87  4997.4  120.43
  4999.6  119.97  5003.2  120.82  5010.3  121.98  5017.1  124.17  5022.2  125.77
    5030  127.86  5152.1   129.9  5172.1   129.8  5252.1   130.7  5272.1   131.4
  5292.1   131.5  5312.1   131.8  5342.1   132.6  5412.1   133.6  5420.2   133.9
#Mann= 6 , 1 , 0
  4493.8      .2       0  4493.8     .15       0  4534.2     .06       0
  4979.1     .04       0    5030     .06       0  5038.6     .06       0
Bank Sta=4995.3,5017.1
Exp/Cntr=0.3,0.1

Type RM Length L Ch R = 1 ,1138.3  ,91.96,111.1,100
BEGIN DESCRIPTION:
Cross Section 1138.3
Cross Section XS-03-bridge1-con
END DESCRIPTION:
XS GIS Cut Line= 5
      3064238.05      13966979.1      3064386.28      13967223.9
      3064389.64      13967415.6      3064410.61       13967624.
      3065093.74       13967718.
#Sta/Elev= 30
  4373.7   130.3  4393.7   129.8  4543.7   129.4  4679.9   127.8  4719.9   128.8
  4749.9   128.2  4851.6     128  4871.6   127.8 4874.15   126.6 4876.15  127.21
 4970.85  127.45 4995.05  120.22 5000.25  117.15 5003.75  115.81 5007.85  116.62
 5009.85  119.21 5013.95   121.2 5020.85  123.51 5029.15  127.51 5070.35  127.87
    5091     127    5121   127.6    5211   127.1    5241   127.7  5338.3  127.32
    5581   131.2    5611   131.2  5717.1  133.76    5741   133.6  5750.6   134.4
#Mann= 5 ,-1 , 0
  4373.7     .15       0 4970.85     .04       0 5029.15     .15       0
  5338.3    .095       0  5717.1     .15       0
Bank Sta=4995.05,5013.95
Exp/Cntr=0.5,0.3

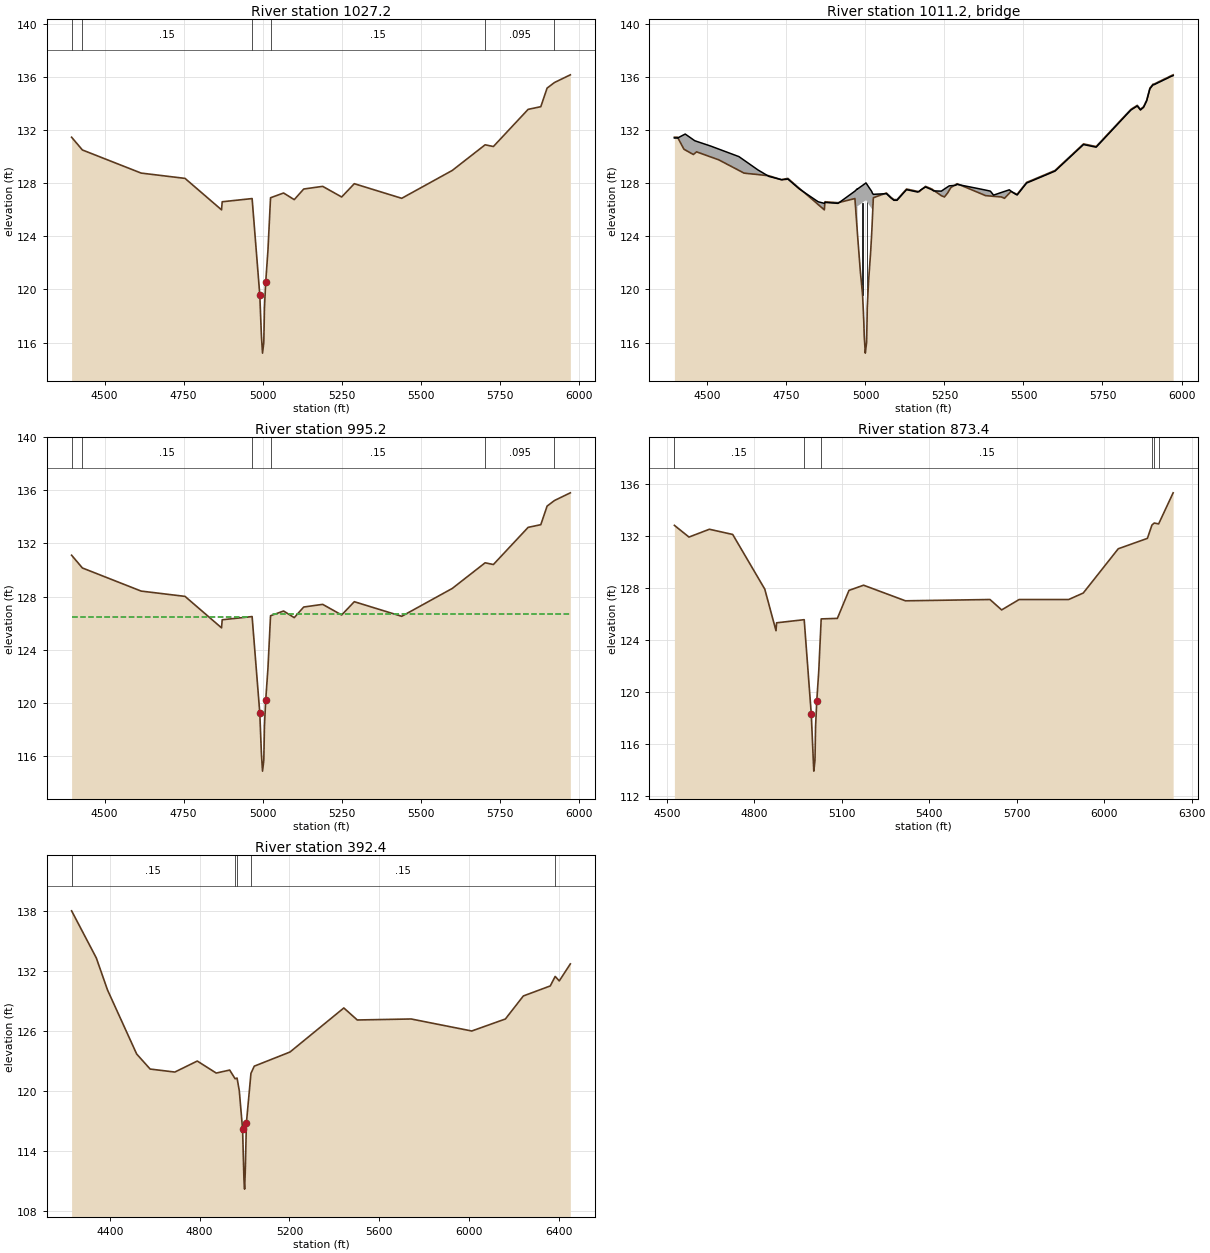
Type RM Length L Ch R = 1 ,1027.2  ,32,32,32
BEGIN DESCRIPTION:
Upstream Section of Access Road Bridge
END DESCRIPTION:
XS GIS Cut Line= 5
      3064174.98      13967006.5      3064333.98      13967272.5
      3064290.83      13967608.8      3064321.79      13967662.5
      3065098.72      13967782.7
#Sta/Elev= 30
  4395.6  131.46  4429.8   130.5  4615.6  128.76  4754.5  128.36    4870  125.99
    4872   126.6  4966.7  126.84  4990.9  119.61  4996.1  116.54  4999.6   115.2
  5003.7  116.01  5005.7   118.6  5009.8  120.59  5016.7   122.9    5025   126.9
  5066.2  127.26    5100  126.76    5130  127.56    5190  127.76    5250  126.96
    5290  127.96    5440  126.86    5600  128.96  5703.9  130.89    5730  130.76
    5840  133.56    5880  133.76    5900  135.16  5923.2  135.58  5973.5  136.16
#Mann= 6 ,-1 , 0
  4395.6      .2       0  4429.8     .15       0  4966.7     .04       0
    5025     .15       0  5703.9    .095       0  5923.2     .15       0
#XS Ineff= 2 , 0
       0  4956.7  126.48    5035       0  126.71
Permanent Ineff=
       F       F
Bank Sta=4990.9,5009.8
Exp/Cntr=0.5,0.3

Type RM Length L Ch R = 3 ,1011.2  ,,,
BEGIN DESCRIPTION:
ACCESS ROAD OF LENZE ROAD (NORTH)
Cross Section 1011.2
Structure ID: M108-00-00-01
END DESCRIPTION:
Bridge Culvert--1,0,-1,-1, 0
Deck Dist Width WeirC Skew NumUp NumDn MinLoCord MaxHiCord MaxSubmerge Is_Ogee
10,12,2.6,0, 110, 110, , , 0.95, 0, 1,1,,
  4395.6  4405.6  4429.8  4455.6  4459.8  4465.6  4509.8  4599.8  4659.8  4694.5
  4734.5  4749.8  4750.4  4754.5  4760.4  4790.4  4850.4    4870    4872  4900.4
  4912.6  4913.5  4966.7  4974.3  4974.4 4974.51 4974.59  4974.7  4974.8 4974.91
  4975.3  4975.4  4984.1  4990.9  4993.5  4995.1  4996.1  4999.6  5001.8  5003.7
  5004.9  5005.4  5005.7  5009.8  5016.7  5020.3 5021.59    5025  5066.2    5069
  5080.5    5090    5100  5115.3    5130  5165.3    5170  5175.3    5190    5210
  5215.3    5240    5250    5260  5265.3  5285.3    5290  5355.3    5380  5395.3
  5405.3    5430    5440  5455.3    5460  5475.3    5480  5495.3    5510  5525.3
  5545.3  5575.3    5600  5605.3    5690  5695.3  5703.9  5715.3    5730  5805.3
  5825.3    5840    5860    5870  5875.3    5880    5890  5895.3    5900  5905.3
    5910  5912.7  5915.3  5923.2  5925.3  5935.3  5945.3  5955.3  5965.3  5973.5
   131.4   131.4   131.7  131.27   131.2  131.15   130.8     130     129  128.51
  128.26  128.29  128.29  128.31  128.19  127.57   126.6  126.48  126.55   126.5
  126.48  126.48   127.4  127.58  127.56  127.56  127.56  127.56  127.56  127.56
  127.57  127.57  127.72  127.83  127.88  127.91  127.92  127.98  128.02  127.95
  127.91  127.89  127.88  127.73  127.49  127.36  127.26  127.16  127.21  127.15
  126.89  126.71  126.71  127.12  127.51  127.33  127.39   127.5  127.71  127.51
  127.42   127.4  127.56  127.72   127.8  127.84  127.91   127.6  127.48   127.4
   127.1   127.3  127.38   127.5  127.41  127.16  127.11  127.57  128.01  128.16
  128.36  128.66  128.91  129.03  130.91  130.88  130.84  130.78  130.71  132.63
  133.14  133.51  133.81  133.51  133.62  133.71  134.21  134.69  135.11  135.27
  135.41  135.41  135.44  135.53  135.56  135.67  135.79   135.9  136.02   136.1
                                                                                
                                                                                
                                                                  126.26  126.26
  126.27  126.27  126.42  126.53  126.58  126.61  126.62  126.68  126.72  126.65
  126.61  126.59  126.58  126.43  126.19  126.06  125.96
                                                                                
                                                                                
                                                                                
                                                                                
                                                                                
                                                                                
  4395.6  4405.6  4429.8  4455.6  4459.8  4465.6  4509.8  4599.8  4659.8  4694.5
  4734.5  4749.8  4750.4  4754.5  4760.4  4790.4  4850.4    4870    4872  4900.4
  4912.6  4913.5  4966.7  4974.3  4974.4 4974.51 4974.59  4974.7  4974.8 4974.91
  4975.3  4975.4  4984.1  4990.9  4993.5  4995.1  4996.1  4999.6  5001.8  5003.7
  5004.9  5005.4  5005.7  5009.8  5016.7  5020.3 5021.59    5025  5066.2    5069
  5080.5    5090    5100  5115.3    5130  5165.3    5170  5175.3    5190    5210
  5215.3    5240    5250    5260  5265.3  5285.3    5290  5355.3    5380  5395.3
  5405.3    5430    5440  5455.3    5460  5475.3    5480  5495.3    5510  5525.3
  5545.3  5575.3    5600  5605.3    5690  5695.3  5703.9  5715.3    5730  5805.3
  5825.3    5840    5860    5870  5875.3    5880    5890  5895.3    5900  5905.3
    5910  5912.7  5915.3  5923.2  5925.3  5935.3  5945.3  5955.3  5965.3  5973.5
   131.4   131.4   131.7  131.27   131.2  131.15   130.8     130     129  128.51
  128.26  128.29  128.29  128.31  128.19  127.57   126.6  126.48  126.55   126.5
  126.48  126.48   127.4  127.58  127.56  127.56  127.56  127.56  127.56  127.56
  127.57  127.57  127.72  127.83  127.88  127.91  127.92  127.98  128.02  127.95
  127.91  127.89  127.88  127.73  127.49  127.36  127.26  127.16  127.21  127.15
  126.89  126.71  126.71  127.12  127.51  127.33  127.39   127.5  127.71  127.51
  127.42   127.4  127.56  127.72   127.8  127.84  127.91   127.6  127.48   127.4
   127.1   127.3  127.38   127.5  127.41  127.16  127.11  127.57  128.01  128.16
  128.36  128.66  128.91  129.03  130.91  130.88  130.84  130.78  130.71  132.63
  133.14  133.51  133.81  133.51  133.62  133.71  134.21  134.69  135.11  135.27
  135.41  135.41  135.44  135.53  135.56  135.67  135.79   135.9  136.02   136.1
                                                                                
                                                                                
                                                                  126.05  126.05
  126.06  126.06  126.21  126.32  126.37   126.4  126.41  126.47  126.51  126.44
   126.4  126.38  126.37  126.22  125.98  125.85  125.75
                                                                                
                                                                                
                                                                                
                                                                                
                                                                                
                                                                                
Pier Skew, UpSta & Num, DnSta & Num=  ,4990.9, 2 ,4990.9, 2 , 0 , 0 , 0 ,,
       1       1
   118.3  127.54
       1       1
  118.09  127.33
Pier Skew, UpSta & Num, DnSta & Num=  ,5005.7, 2 ,5005.7, 2 , 0 , 0 , 0 ,,
       1       1
  116.75   127.6
       1       1
  116.54  127.39
Abutment Skew #Up #Dn= , 2 , 2
  5020.4 5021.79
  124.43  125.96
  5020.4 5021.79
  124.22  125.75
BR Coef= 1 , 1 , 1 ,1.25, 0 ,,,0.8,0,2,0,
WSPro=,,,, 1 ,,,, 0 ,,,, 0 ,,,,-1 ,-1 ,-1 , 0 , 0 , 0 , 0 , 0
BR U #Sta/Elev= 126
  4395.6  131.46  4405.6  131.46  4425.6  130.56  4429.8   130.5  4455.6  130.16
  4459.8  130.24  4465.6  130.36  4509.8  129.98  4529.8  129.81  4535.6  129.76
  4599.8  128.96  4615.6  128.76  4629.8  128.72  4659.8  128.65  4669.8  128.62
  4694.5  128.56  4734.5  128.26  4749.8  128.34  4750.4  128.34  4754.5  128.36
  4760.4  128.24  4790.4  127.62  4820.4  127.01  4840.4   126.6  4850.4  126.39
    4870  125.99    4872   126.6  4900.4  126.55  4912.6  126.53  4913.5  126.53
  4966.7  126.84  4974.3  124.34  4974.4  124.31 4974.51  124.27 4974.59  124.24
  4974.7  124.21  4974.8  124.17 4974.91  124.14  4975.3  124.01  4975.4  123.98
  4984.1   121.3  4990.9  119.61  4993.5  118.31  4995.1   117.4  4996.1  116.54
  4999.6   115.2  5001.8  115.63  5003.7  116.01  5004.9  117.43  5005.4  118.06
  5005.7   118.6  5009.8  120.59  5016.7   122.9  5020.3  124.44  5020.4  124.49
  5021.1  124.86 5021.19  124.91  5021.3  124.96 5021.41  125.02  5021.5  125.07
 5021.59  125.12  5021.7  125.17    5025   126.9  5066.2  127.26    5069   127.2
  5080.5  126.94    5090  126.76    5100  126.76  5115.3  127.17    5130  127.56
  5165.3  127.38    5170  127.36  5175.3  127.47    5190  127.76    5210  127.56
  5215.3  127.47    5240  127.06    5250  126.96    5260  127.26  5265.3  127.47
    5270  127.66  5285.3  127.89    5290  127.96  5355.3  127.31    5380  127.06
  5395.3  127.03  5405.3  127.01    5430  126.96    5440  126.86  5455.3  127.24
    5460  127.36  5475.3  127.21    5480  127.16  5495.3  127.62    5510  128.06
  5525.3  128.21  5545.3  128.41  5575.3  128.71    5600  128.96  5605.3  129.08
    5690  130.96  5695.3  130.93  5703.9  130.89  5715.3  130.83    5730  130.76
  5805.3  132.68  5825.3  133.19    5840  133.56    5860  133.86    5870  133.56
  5875.3  133.67    5880  133.76    5890  134.26  5895.3  134.74    5900  135.16
  5905.3  135.32    5910  135.46  5912.7  135.46  5915.3  135.49  5923.2  135.58
  5925.3  135.61  5935.3  135.72  5945.3  135.84  5955.3  135.95  5965.3  136.07
  5973.5  136.16
BR U #Mann= 6
  4395.6      .2  4429.8     .15  4966.7     .03    5025     .15  5703.9    .095
  5923.2     .15
BR D #Sta/Elev= 126
  4395.6  131.11  4405.6  131.11  4425.6  130.21  4429.8  130.15  4455.6  129.81
  4459.8  129.89  4465.6  130.01  4509.8  129.63  4529.8  129.46  4535.6  129.41
  4599.8  128.61  4615.6  128.41  4629.8  128.37  4659.8   128.3  4669.8  128.27
  4694.5  128.21  4734.5  127.91  4749.8  127.99  4750.4  127.99  4754.5  128.01
  4760.4  127.89  4790.4  127.27  4820.4  126.66  4840.4  126.25  4850.4  126.04
    4870  125.64    4872  126.25  4900.4   126.2  4912.6  126.18  4913.5  126.18
  4966.7  126.49  4974.3  123.99  4974.4  123.96 4974.51  123.92 4974.59  123.89
  4974.7  123.86  4974.8  123.82 4974.91  123.79  4975.3  123.66  4975.4  123.63
  4984.1  120.95  4990.9  119.26  4993.5  117.96  4995.1  117.05  4996.1  116.19
  4999.6  114.85  5001.8  115.28  5003.7  115.66  5004.9  117.08  5005.4  117.71
  5005.7  118.25  5009.8  120.24  5016.7  122.55  5020.3  124.09  5020.4  124.14
  5021.1  124.51 5021.19  124.56  5021.3  124.61 5021.41  124.67  5021.5  124.72
 5021.59  124.77  5021.7  124.82    5025  126.55  5066.2  126.91    5069  126.85
  5080.5  126.59    5090  126.41    5100  126.41  5115.3  126.82    5130  127.21
  5165.3  127.03    5170  127.01  5175.3  127.12    5190  127.41    5210  127.21
  5215.3  127.12    5240  126.71    5250  126.61    5260  126.91  5265.3  127.12
    5270  127.31  5285.3  127.54    5290  127.61  5355.3  126.96    5380  126.71
  5395.3  126.68  5405.3  126.66    5430  126.61    5440  126.51  5455.3  126.89
    5460  127.01  5475.3  126.86    5480  126.81  5495.3  127.27    5510  127.71
  5525.3  127.86  5545.3  128.06  5575.3  128.36    5600  128.61  5605.3  128.73
    5690  130.61  5695.3  130.58  5703.9  130.54  5715.3  130.48    5730  130.41
  5805.3  132.33  5825.3  132.84    5840  133.21    5860  133.51    5870  133.21
  5875.3  133.32    5880  133.41    5890  133.91  5895.3  134.39    5900  134.81
  5905.3  134.97    5910  135.11  5912.7  135.11  5915.3  135.14  5923.2  135.23
  5925.3  135.26  5935.3  135.37  5945.3  135.49  5955.3   135.6  5965.3  135.72
  5973.5  135.81
BR D #Mann= 6
  4395.6      .2  4429.8     .15  4966.7     .03    5025     .15  5703.9    .095
  5923.2     .15
BC Design=,, 0 ,, 0 ,,,,,,
BC HTab HWMax=136.16

Type RM Length L Ch R = 1 ,995.2   ,121.8,121.8,121.8
BEGIN DESCRIPTION:
Downstream Section of Access Road Bridge
END DESCRIPTION:
XS GIS Cut Line= 4
       3064095.3      13967069.3      3064294.16      13967320.8
      3064247.27      13967682.7      3065092.82      13967829.3
#Sta/Elev= 30
  4395.6  131.11  4429.8  130.15  4615.6  128.41  4754.5  128.01    4870  125.64
    4872  126.25  4966.7  126.49  4990.9  119.26  4996.1  116.19  4999.6  114.85
  5003.7  115.66  5005.7  118.25  5009.8  120.24  5016.7  122.55    5025  126.55
  5066.2  126.91    5100  126.41    5130  127.21    5190  127.41    5250  126.61
    5290  127.61    5440  126.51    5600  128.61  5703.9  130.54    5730  130.41
    5840  133.21    5880  133.41    5900  134.81  5923.2  135.23  5973.5  135.81
#Mann= 6 ,-1 , 0
  4395.6      .2       0  4429.8     .15       0  4966.7     .04       0
    5025     .15       0  5703.9    .095       0  5923.2     .15       0
#XS Ineff= 2 , 0
       0 4960.03  126.48 5031.67       0  126.71
Permanent Ineff=
       F       F
Bank Sta=4990.9,5009.8
Exp/Cntr=0.5,0.3

Type RM Length L Ch R = 1 ,873.4   ,493.63,481,466.43
BEGIN DESCRIPTION:
Cross Section 873.4
Cross Section XS-02-bridge1-exp
END DESCRIPTION:
XS GIS Cut Line= 4
      3063955.07      13967134.1      3064157.13      13967430.7
      3064116.61       13967762.       3065116.2      13967956.1
#Sta/Elev= 30
  4525.6   132.8  4575.6   131.9  4645.6   132.5  4725.6   132.1  4835.6   127.9
 4874.15   124.7 4876.15  125.31 4970.85  125.55 4995.05  118.32 5003.75  113.91
 5007.85  114.72 5009.85  117.31 5013.95   119.3 5020.85  121.61 5029.15  125.61
 5084.65  125.65  5124.5   127.8  5174.5   128.2  5318.2     127  5608.2   127.1
  5648.2   126.3  5708.2   127.1  5878.2   127.1  5928.2   127.6  6048.2     131
  6148.2   131.8  6163.7  132.82  6171.6  132.98  6186.7  132.91  6236.5   135.3
#Mann= 6 ,-1 , 0
  4525.6     .15       0 4970.85     .04       0 5029.15     .15       0
  6163.7    .095       0  6171.6     .15       0  6186.7     .08       0
Bank Sta=4995.05,5013.95
Exp/Cntr=0.3,0.1

Type RM Length L Ch R = 1 ,392.4   ,0,0,0
BEGIN DESCRIPTION:
Cross Section 392.4
Cross Section XS-01
END DESCRIPTION:
XS GIS Cut Line= 4
      3063392.65      13967053.7      3063654.53      13967642.5
      3063810.27       13967849.      3065114.72      13968047.1
#Sta/Elev= 30
  4229.4     138  4339.4   133.3  4389.4   130.1  4519.4   123.7  4579.4   122.2
  4689.4   121.9  4789.4     123  4873.8   121.8  4933.8   122.1  4958.1  121.23
  4966.7   121.3  4976.6  120.05  4991.4  116.17  4997.5  111.14  5000.3  110.21
  5003.2  111.89  5008.3   116.8  5028.6  121.77  5043.5  122.49  5202.5   123.9
  5442.5   128.3  5502.5   127.1  5742.5   127.2  6012.5     126  6162.5   127.2
  6242.5   129.5  6362.5   130.5  6384.3  131.45  6402.5     131  6451.9   132.7
#Mann= 5 ,-1 , 0
  4229.4     .15       0  4958.1     .15       0  4966.7     .04       0
  5028.6     .15       0  6384.3     .12       0
Bank Sta=4991.4,5008.3
Exp/Cntr=0.3,0.1

Chan Stop Cuts=-1
Use User Specified Reach Order=0
User Specified Reach Order=M108-00-00      ,Reach - 1